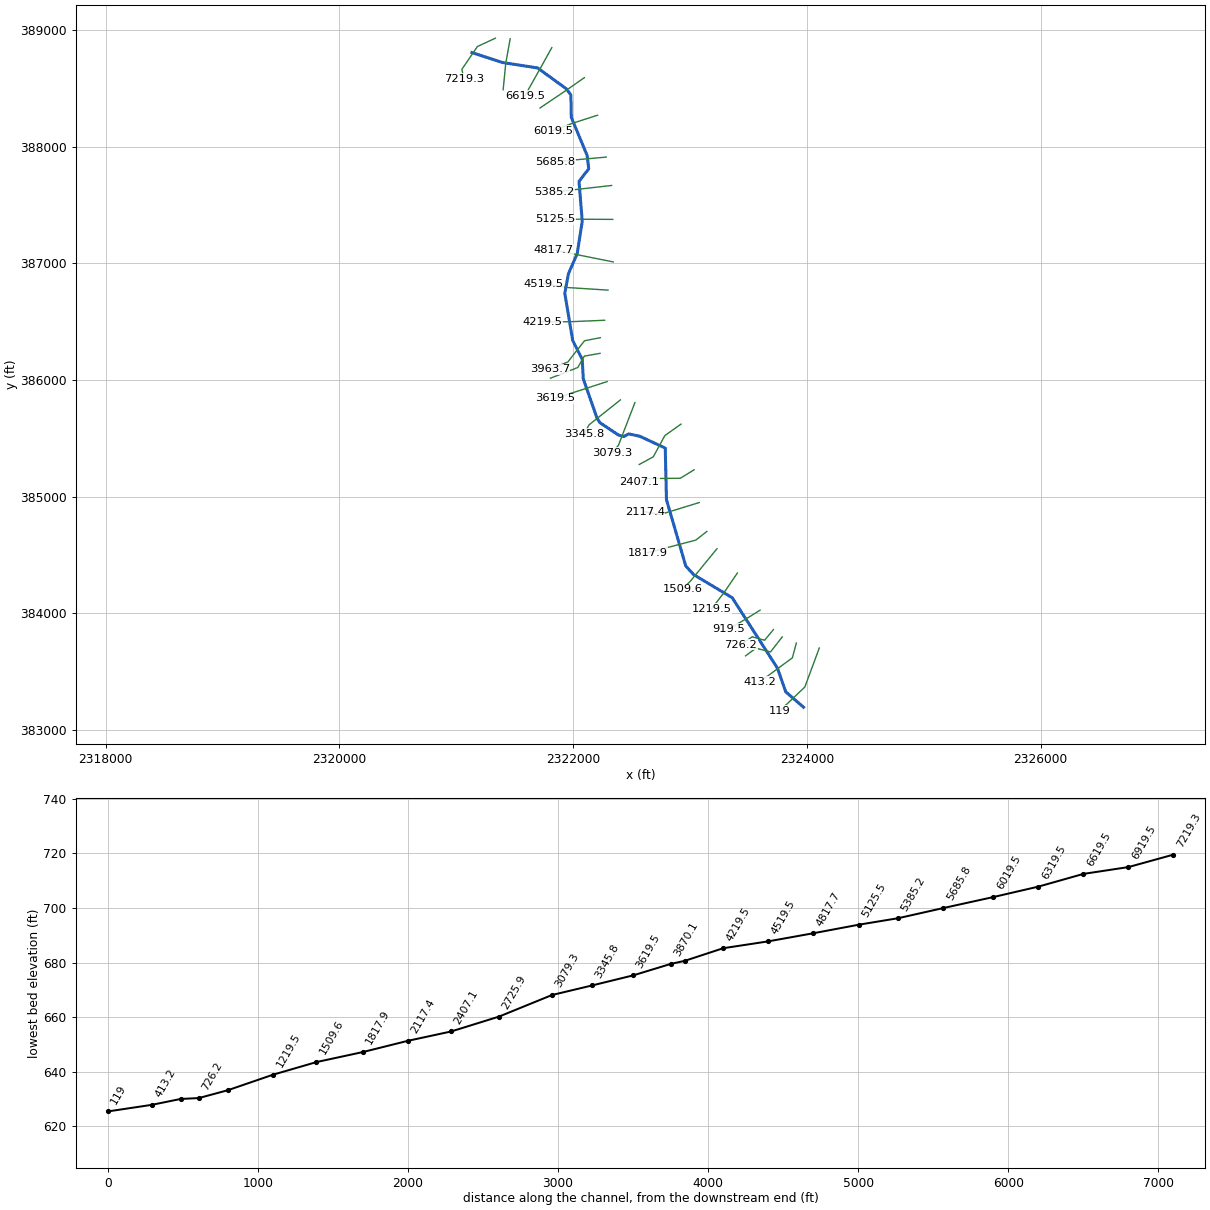
--- SLPYCKTRB1.prj (project) ---

Proj Title=SLPYCKTRB1
Current Plan=p01
Default Exp/Contr=0,0
English Units
Geom File=g01
Flow File=f01
Plan File=p01
BEGIN DESCRIPTION:
END DESCRIPTION:
DSS Export Rating Curves= 0
DSS Export Rating Curve Sorted= 0
DSS Export Volume Flow Curves= 0
DXF OffsetX= 0
DXF OffsetY= 0
DXF ScaleX= 0
DXF ScaleY= 0

--- SLPYCKTRB1.p01 (plan) ---

Plan Title=Floodplain
Program Version=4.00
Geom File=g01
Flow File=f01
K Sum by GR=0
Std Step Tol=0.01
Critical Tol=0.01
Num of Std Step Trials=20
Max Error Tol=0.3
Flow Tol Ratio=0.001
Split Flow NTrial=30
Split Flow Tol=0.02
Split Flow Ratio=0.02
Log Output Level=0
Friction Slope Method=1
Unsteady Friction Slope Method=2
Unsteady Bridges Friction Slope Method=1
Global Log Level=0
CheckData=False
Run HTab=0
Run UNet=0
Run PostProcess=0
UNET Theta=0
UNET Theta Warmup=0
UNET ZTol=0
UNET ZSATol=0
UNET MxIter=0
UNET MaxInSteps=0
UNET DtIC=0
UNET DtMin=0
UNET MaxCRTS=0
UNET WFStab=0
UNET SFStab=0
UNET WFX=0
UNET SFX=0
UNET DSS MLevel=0
UNET DZMax Abort=0
UNET Convert EG Bridges=0
UNET Use Existing IB Tables=0
UNET Froude Limit=0
UNET Froude Power=0
Write IC File=0
Echo Input=False
Echo Output=False
Write Detailed=0

--- SLPYCKTRB1.f01 (steady flow) ---

Flow Title=NFF Regression Equation
Program Version=4.00
Number of Profiles=1
Profile Names=P100yr
River Rch & RM=SLPYCKTRB1,Main      ,7219.3
607.7844
River Rch & RM=SLPYCKTRB1,Main      ,6319.5
665.1967
River Rch & RM=SLPYCKTRB1,Main      ,3345.8
716.6453
River Rch & RM=SLPYCKTRB1,Main      ,3079.3
818.0572
River Rch & RM=SLPYCKTRB1,Main      ,919.5
874.0316
River Rch & RM=SLPYCKTRB1,Main      ,726.2
975.0194
Boundary for River Rch & Prof#=SLPYCKTRB1,Main      ,1
Up Type=0
Dn Type=3
Dn Slope=0.007419

--- SLPYCKTRB1.g01 (geometry) ---

Geom Title=USGS 10m DEM
Program Version=4.10

River Reach=SLPYCKTRB1      ,Main
Reach XY= 30
2321133.75733839388806.724779844 2321394.1738123388721.655396178
2321696.25719763388674.7804899222321944.52113681388494.224748671
2321980.97939722388442.1415195022321984.45150314388251.169132426
2322119.86822705387924.7803495082322133.75730689387810.196917251
2322050.42381214387702.5580249282322078.20164372387360.544273257
2322034.79884338387082.7666135882321960.14610556386910.891629264
2321928.89616805386742.4887508452321996.60436597386337.974796087
2322078.20164372386176.5164575872322086.88207255386009.849796176
 2322203.2017218385676.5164733382322227.50711939385634.849890009
2322388.96545789385527.2109976712322432.36825822385515.058134839
2322475.77105856385537.6276435112322571.25708805385516.794351846
2322788.27108972385416.0999994282322798.68773556 384973.39156726
2322963.61817996 384405.683057012323031.32670596384331.030319169
 2323361.1875948384133.1137202532323748.34069188383528.946949586
2323819.52099572383325.8220277582323971.64339489383194.012580097

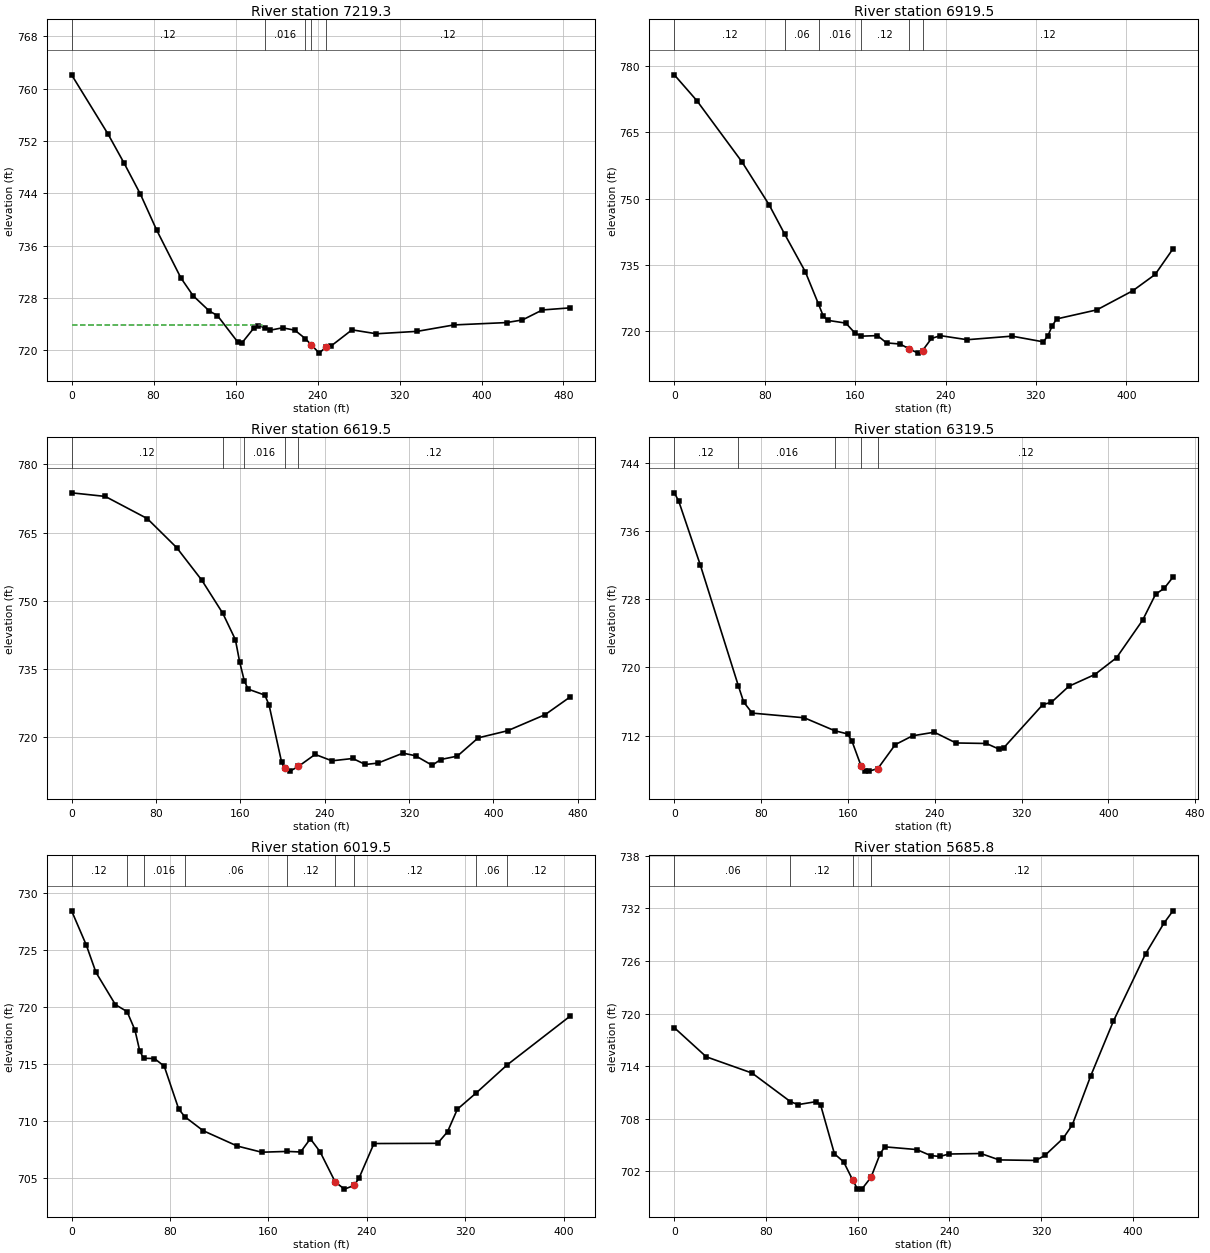
Type RM Length L Ch R = 1 ,7219.3  ,283.3,299.8,319.3
XS GIS Cut Line= 4
     2321334.814      388929.769     2321180.645      388858.147
       2321048.7      388663.702      2321063.62      388583.512
#Sta/Elev= 30
       0   762.1    35.6  753.03    51.4  748.55    67.2  743.84      83  738.37
   106.7  731.04   118.6  728.33   134.4     726   142.3   725.3   162.1  721.26
     166  721.08     178  723.42   181.9  723.77  188.84723.4537   193.9  723.07
   205.8  723.43   217.8  723.07  228.17721.7657   233.7  720.85   241.7  719.56
   248.7  720.57   253.6   720.7   273.6  723.12   297.4  722.52   337.3  722.89
   373.1  723.87   424.4  724.23   439.9  724.63   459.4  726.16   486.6  726.48
#Mann= 5 ,-1 , 0
       0     .12       0  188.84    .016       0  228.17     .12       0
   233.7    .045       0   248.7     .12       0
#XS Ineff= 2 , 0
       0   185.9  723.88               0
Permanent Ineff=
       F       F
Bank Sta=233.7,248.7
XS Rating Curve= 0 ,0
Exp/Cntr=0.3,0.1

Type RM Length L Ch R = 1 ,6919.5  ,312.4,300,284.4
XS GIS Cut Line= 3
     2321461.499      388924.836     2321423.958      388716.447
     2321401.456      388487.977
#Sta/Elev= 30
       0  778.07      20   772.2    59.9  758.34    83.9  748.62   97.71741.9476
   115.9  733.46  127.62726.1078   131.8  723.41   135.8  722.43   151.8   721.8
   159.8  719.56  165.61718.8442   179.8  718.97   187.8  717.32   199.8  717.06
   207.8  715.98   215.7     715   219.7  715.59   227.6  718.33   235.5  718.96
   259.2  718.04   298.8  718.85   326.5  717.56   330.5  718.86   334.4  721.18
   338.4  722.75     374  724.81   405.7  729.13   425.5  732.82   441.3  738.63
#Mann= 6 ,-1 , 0
       0     .12       0   97.71     .06       0  127.62    .016       0
  165.61     .12       0   207.8    .045       0   219.7     .12       0
Bank Sta=207.8,219.7
XS Rating Curve= 0 ,0
Exp/Cntr=0.3,0.1

Type RM Length L Ch R = 1 ,6619.5  ,318.2,300,279
XS GIS Cut Line= 3
     2321817.746      388848.755     2321715.235      388664.237
     2321587.176      388436.019
#Sta/Elev= 30
       0  773.74    31.9  772.95    71.7  768.08    99.6  761.69   123.5   754.5
   143.4  747.21   155.3  741.43   159.3  736.58  163.67732.4285   167.3  730.55
   183.2  729.23   187.2  727.07   199.1  714.49  201.97713.1913   207.1   712.5
     215  713.53   230.9  716.18   246.8  714.77   266.6  715.28   278.5  713.96
   290.4  714.27   314.2  716.46   326.1  715.88   341.9  713.78   349.9  715.05
   365.7   715.8   385.5  719.82   413.3  721.38     449  724.93   472.8  728.84
#Mann= 5 ,-1 , 0
       0     .12       0   143.4     .08       0  163.67    .016       0
  201.97    .045       0     215     .12       0
Bank Sta=201.97,215
XS Rating Curve= 0 ,0
Exp/Cntr=0.3,0.1

Type RM Length L Ch R = 1 ,6319.5  ,313.1,300,291.2
XS GIS Cut Line= 3
      2322095.84      388591.286     2321948.684      388488.277
     2321716.804      388331.413
#Sta/Elev= 30
       0  740.45       4   739.5      24  731.98   58.98717.8572    63.9  715.94
    71.8  714.64   119.8  714.09  147.85 712.574   159.7   712.2   163.7  711.37
   172.1  708.46   175.6  707.85   179.6  707.84   187.6  708.14   203.6  710.94
   219.6  711.98   239.6   712.4   259.6  711.14   287.6  711.08   299.6   710.4
   303.6  710.57   339.6  715.63   347.6  715.91   363.6  717.78   387.6  719.16
   407.6  721.13   431.6  725.52   443.6  728.57   451.6  729.27   459.6  730.57
#Mann= 5 ,-1 , 0
       0     .12       0   58.98    .016       0  147.85     .12       0
   172.1    .045       0   187.6     .12       0
Bank Sta=172.1,187.6
XS Rating Curve= 0 ,0
Exp/Cntr=0.3,0.1

Type RM Length L Ch R = 1 ,6019.5  ,342.2,333.7,323.4
XS GIS Cut Line= 3
     2322209.257       388269.57     2321998.159      388201.481
     2321826.358       388136.82
#Sta/Elev= 30
       0  728.44    11.9  725.45    19.8  723.04    35.6  720.21   45.09719.5981
    51.5  717.98    55.4  716.14   58.55715.5021    67.3  715.48    75.3  714.81
    87.1  711.04   92.11710.3666   106.9  709.15   134.7   707.8   154.5  707.26
  175.09 707.328   186.2  707.28   194.1  708.44     202   707.3   214.3  704.65
   221.8  704.02   229.8  704.35   233.8  705.02   245.8  708.02   297.6  708.04
   305.6  709.05   313.6  711.03  328.99712.4651  354.03714.9149   405.4  719.21
#Mann= 9 ,-1 , 0
       0     .12       0   45.09     .06       0   58.55    .016       0
   92.11     .06       0  175.09     .12       0   214.3    .045       0
   229.8     .12       0  328.99     .06       0  354.03     .12       0
Bank Sta=214.3,229.8
XS Rating Curve= 0 ,0
Exp/Cntr=0.3,0.1

Type RM Length L Ch R = 1 ,5685.8  ,298.1,300.6,302.9
XS GIS Cut Line= 2
     2322283.623       387910.63     2321850.369      387871.581
#Sta/Elev= 30
       0  718.39    27.9  715.07    67.8  713.22  101.21709.9713   107.8  709.62
   123.7  709.96   127.7  709.55   139.7  704.01   147.7   703.1   155.6  701.03
   159.6  700.05   163.6  699.99   171.6  701.34   179.6  704.03   183.6  704.81
   211.5   704.5   223.5  703.82   231.5  703.71   239.5  703.99   267.4  704.05
   283.4  703.32   315.3  703.26   323.3  703.83   339.2  705.78   347.2  707.32
   363.2  712.88   383.1  719.16   411.1  726.81     427  730.28     435  731.71
#Mann= 4 ,-1 , 0
       0     .06       0  101.21     .12       0   155.6    .045       0
   171.6     .12       0
Bank Sta=155.6,171.6
XS Rating Curve= 0 ,0
Exp/Cntr=0.3,0.1

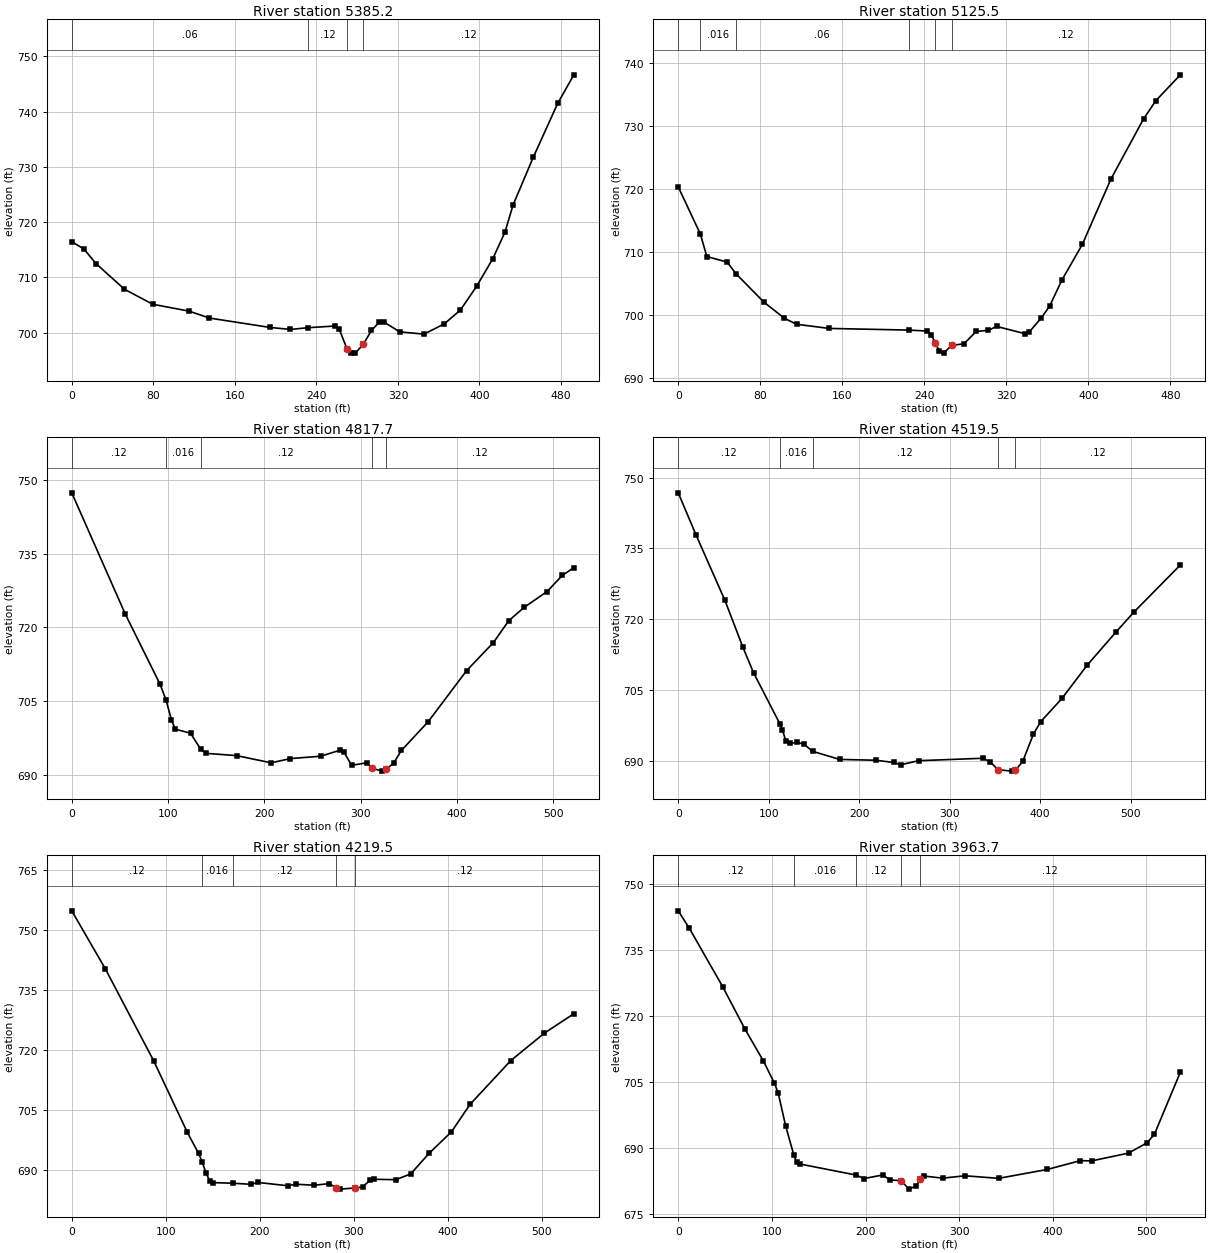
Type RM Length L Ch R = 1 ,5385.2  ,264.1,259.7,255.2
XS GIS Cut Line= 2
     2322329.475        387667.4     2321840.093      387611.564
#Sta/Elev= 30
       0  716.45    11.9  715.13    23.8  712.48    51.6  707.85    79.4  705.12
   115.2  703.87   135.1  702.62   194.6  700.92   214.5  700.56  231.54  700.87
   258.2  701.18   262.2  700.71   270.1     697   274.1  696.27   278.1  696.28
     286  697.84     294  700.38   301.9   701.9   305.9  701.94   321.8  700.12
   345.6  699.71   365.4  701.56   381.3  704.07   397.2  708.37   413.1  713.37
     425  718.17     433  723.11   452.8  731.74   476.7  741.48   492.6  746.67
#Mann= 4 ,-1 , 0
       0     .06       0  231.54     .12       0   270.1    .045       0
     286     .12       0
Bank Sta=270.1,286
XS Rating Curve= 0 ,0
Exp/Cntr=0.3,0.1

Type RM Length L Ch R = 1 ,5125.5  ,314.9,307.8,300.7
XS GIS Cut Line= 2
     2322339.291      387376.347     2321849.627      387378.877
#Sta/Elev= 30
       0  720.31   21.55 712.834    27.9  709.25    47.8  708.37   56.12706.5576
    83.6  702.01   103.5  699.46   115.4   698.5   147.3  697.84  224.69697.5797
   242.8  697.42   246.8  696.85   250.8  695.54   254.8   694.2   258.8  693.92
   266.7  695.15   278.7   695.4   290.6  697.36   302.6  697.54   310.5  698.16
   338.4     697   342.4  697.28   354.3  699.54   362.3   701.4   374.2  705.52
   394.1  711.17     422  721.55   453.8  731.09   465.8  733.99   489.7   738.1
#Mann= 6 ,-1 , 0
       0     .12       0   21.55    .016       0   56.12     .06       0
  224.69     .12       0   250.8    .045       0   266.7     .12       0
#XS Ineff= 2 , 0
       0   163.2                       0
Permanent Ineff=
       F       F
Bank Sta=250.8,266.7
XS Rating Curve= 0 ,0
Exp/Cntr=0.3,0.1

Type RM Length L Ch R = 1 ,4817.7  ,293.4,298.2,299.5
XS GIS Cut Line= 2
     2322343.343      387011.754     2321832.066      387114.232
#Sta/Elev= 30
       0  747.39    55.7  722.65    91.6  708.46   97.97705.1921   103.5  701.15
   107.5  699.28   123.4  698.45  133.85695.1807   139.3  694.36   171.2   693.9
     207  692.43   226.9  693.29   258.7  693.78   278.6     695   282.6  694.66
   290.6  691.92   306.5  692.44   311.6  691.33   322.4  690.74   326.6  691.09
   334.4  692.42   342.3  694.94   370.2  700.82     410  711.19   437.9  716.92
   453.8  721.36   469.7  724.06   493.6   727.3   509.5   730.6   521.4  732.14
#Mann= 5 ,-1 , 0
       0     .12       0   97.97    .016       0  133.85     .12       0
   311.6    .045       0   326.6     .12       0
Bank Sta=311.6,326.6
XS Rating Curve= 0 ,0
Exp/Cntr=0.3,0.1

Type RM Length L Ch R = 1 ,4519.5  ,295.9,300,306.2
XS GIS Cut Line= 3
     2322298.593      386770.141     2321938.382      386793.099
     2321746.715      386823.766
#Sta/Elev= 30
       0  746.77    19.8  737.79    51.6  723.98    71.4  714.08    83.3  708.62
  112.47697.7677     115   696.6     119  694.16     123  693.65   130.9  693.89
   138.8  693.52  148.49691.9883   178.5  690.27   218.2   690.1     238  689.63
   245.9  689.14   265.8     690   337.1  690.52   345.1   689.7   353.4   688.1
   368.4  687.79   372.8  687.96   380.8  689.85   392.6  695.62   400.6  698.25
   424.3  703.22     452  710.24   483.7  717.22   503.6  721.48     555  731.47
#Mann= 5 ,-1 , 0
       0     .12       0  112.47    .016       0  148.49     .12       0
   353.4    .045       0   372.8     .12       0
Bank Sta=353.4,372.8
XS Rating Curve= 0 ,0
Exp/Cntr=0.3,0.1

Type RM Length L Ch R = 1 ,4219.5  ,221.7,255.8,290.5
XS GIS Cut Line= 3
     2322269.181      386511.699      2321971.87      386499.089
     2321735.129      386498.204
#Sta/Elev= 30
       0  754.78    35.7   740.3    87.3  717.26     123  699.45   134.9  694.21
  138.76692.1159   142.8  689.32   146.8  687.36   150.8   686.9  171.22686.7569
   190.4  686.49   198.4  686.94   230.1  686.12   238.1  686.51   257.9  686.26
   273.8  686.64   281.7  685.64   285.7  685.28   301.5  685.57   309.4  685.82
   317.3  687.46   321.2  687.74   344.9  687.64   360.7  689.08   380.4  694.26
   404.1   699.6   423.8  706.44   467.2  717.38   502.8  724.21   534.3  729.08
#Mann= 5 ,-1 , 0
       0     .12       0  138.76    .016       0  171.22     .12       0
   281.7    .045       0   301.5     .12       0
Bank Sta=281.7,301.5
XS Rating Curve= 0 ,0
Exp/Cntr=0.3,0.1

Type RM Length L Ch R = 1 ,3963.7  ,93.8,93.6,125.3
XS GIS Cut Line= 4
     2322233.218      386362.592     2322097.442      386335.794
     2321954.213      386153.503     2321799.835      386092.409
#Sta/Elev= 30
       0  743.87    11.9  739.89    47.4  726.66    71.2  717.03      91  709.75
   102.8  704.67   106.8  702.45   114.7  695.02  123.51688.3617   126.5  686.79
   130.5  686.34  189.44683.8776   198.4  683.06   218.3  683.87   226.3  682.75
   238.3  682.57   246.3  680.66   254.3  681.38   258.3  682.93   262.3  683.64
   282.3  683.15   306.3  683.69   342.2  683.11   393.9  685.12   429.5  687.13
   441.4  687.07   480.9  688.84   500.7  691.19   508.6  693.15   536.2   707.2
#Mann= 5 ,-1 , 0
       0     .12       0  123.51    .016       0  189.44     .12       0
   238.3    .045       0   258.3     .12       0
Bank Sta=238.3,258.3
XS Rating Curve= 0 ,0
Exp/Cntr=0.3,0.1

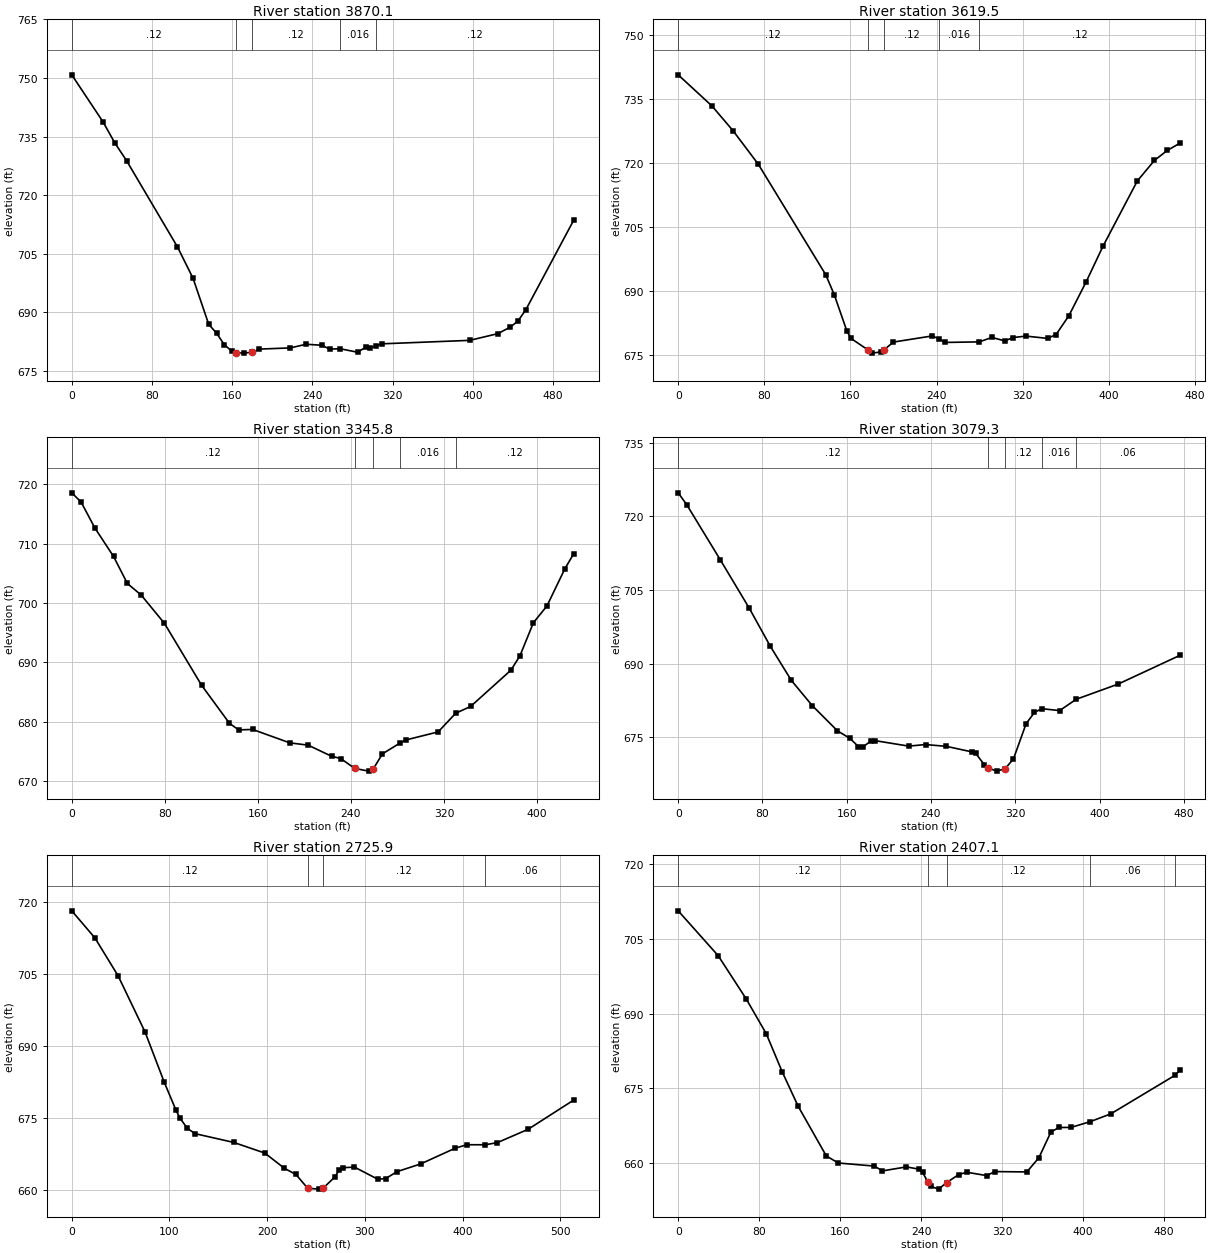
Type RM Length L Ch R = 1 ,3870.1  ,274.5,250.6,195.3
XS GIS Cut Line= 4
     2322230.643      386228.221      2322096.14      386204.284
      2322040.15      386106.628     2321806.058      386014.757
#Sta/Elev= 30
       0   750.8    31.2  738.74    42.9  733.38    54.6  728.84   105.4  706.74
     121  698.67   136.6   686.9   144.4  684.64   152.1   681.7   159.9  679.98
   163.8  679.62   171.6  679.53   180.2  679.78   187.1  680.56   218.1  680.87
   233.7   681.8   249.2  681.55   257.2  680.57  267.66680.6484   285.1  679.76
   293.1  681.04   297.1  680.84   303.4681.3983   309.1  681.91   396.9   682.8
   424.8  684.51   436.8  686.11   444.8  687.68   452.8  690.61   500.7  713.62
#Mann= 5 ,-1 , 0
       0     .12       0   163.8    .045       0   180.2     .12       0
  267.66    .016       0   303.4     .12       0
Bank Sta=163.8,180.2
XS Rating Curve= 0 ,0
Exp/Cntr=0.3,0.1

Type RM Length L Ch R = 1 ,3619.5  ,259.9,273.6,287.1
XS GIS Cut Line= 3
     2322290.782      385985.806     2322115.793       385928.81
     2321847.426      385841.772
#Sta/Elev= 30
       0  740.72    31.3  733.42    50.9   727.6    74.4  719.71     137  693.76
   144.9  689.07   156.6  680.57   160.5  678.78   176.5  676.04   180.1  675.33
     188   675.6   191.5  676.18   199.9  677.93   235.7  679.36  242.04 678.732
   247.6  677.84  279.65677.9744   291.3  679.02   303.2  678.21   311.2     679
   323.1  679.33     343  678.79   350.9  679.69   362.8  684.12   378.8  692.06
   394.6  700.51   426.4   715.8   442.3  720.62   454.2  722.96   466.2   724.7
#Mann= 5 ,-1 , 0
       0     .12       0   176.5    .045       0   191.5     .12       0
  242.04    .016       0  279.65     .12       0
Bank Sta=176.5,191.5
XS Rating Curve= 0 ,0
Exp/Cntr=0.3,0.1

Type RM Length L Ch R = 1 ,3345.8  ,255.9,266.5,286.7
XS GIS Cut Line= 3
     2322404.703      385828.759     2322136.407       385615.25
     2322093.822      385537.365
#Sta/Elev= 30
       0  718.59       8  717.04    19.9  712.65    35.9  707.86    47.8   703.3
    59.8  701.32    79.7  696.56   111.6  686.13   135.6   679.7   143.5   678.6
   155.5  678.67   187.4  676.41   203.3  676.02   223.3  674.15   231.2  673.77
   243.2   672.1   255.2  671.64   259.2  672.01   267.1  674.56  281.94676.3453
   287.1  676.89     315  678.26  330.06681.4061   342.9  682.55   377.6  688.68
   385.3   691.1   396.9  696.69   408.5   699.5   423.9  705.77   431.6  708.34
#Mann= 5 ,-1 , 0
       0     .12       0   243.2    .045       0   259.2     .12       0
  281.94    .016       0  330.06     .12       0
Bank Sta=243.2,259.2
XS Rating Curve= 0 ,0
Exp/Cntr=0.3,0.1

Type RM Length L Ch R = 1 ,3079.3  ,345.9,353.4,348.2
XS GIS Cut Line= 3
     2322528.701      385805.676     2322387.242      385438.008
     2322330.479      385377.933
#Sta/Elev= 30
       0  724.79       8  722.41    39.8  711.22    67.6  701.26    87.5  693.54
   107.4  686.62   127.3  681.48   151.2  676.35   163.2   674.8   171.1  673.14
   175.1  673.02     183  674.29     187  674.35   218.9  673.24   234.8  673.56
   254.7  673.19   278.5  672.08   282.5  671.75   290.5  669.49   294.5  668.78
   302.4  668.15   310.4  668.64   318.3  670.65   330.3   677.8   338.2  680.09
  345.09680.8584   362.1  680.47  377.86682.7725   417.6  685.86   476.6  691.74
#Mann= 5 ,-1 , 0
       0     .12       0   294.5    .045       0   310.4     .12       0
  345.09    .016       0  377.86     .06       0
#XS Ineff= 2 , 0
       0   234.8  673.56               0
Permanent Ineff=
       F       F
Bank Sta=294.5,310.4
XS Rating Curve= 0 ,0
Exp/Cntr=0.3,0.1

Type RM Length L Ch R = 1 ,2725.9  ,359.8,318.8,277.9
XS GIS Cut Line= 4
     2322923.218      385621.238     2322784.812      385523.077
     2322685.853      385340.786     2322565.718      385275.355
#Sta/Elev= 30
       0  718.26    23.7  712.61    47.4  704.72      75  693.01    94.7  682.51
   106.5  676.79   110.5  675.11   118.4  672.89   126.3   671.8   165.7  669.98
   197.6  667.76   217.6  664.59   229.5  663.29   241.5  660.42   253.4  660.24
   257.4  660.46   269.4  662.79   273.4  664.16   277.4   664.7   289.4  664.83
   313.3   662.3   321.3  662.45   333.2   663.9   357.2   665.5   392.7  668.79
   404.5   669.5  423.26669.4848   435.7  669.94     467   672.7   513.9  678.82
#Mann= 4 ,-1 , 0
       0     .12       0   241.5    .045       0   257.4     .12       0
  423.26     .06       0
Bank Sta=241.5,257.4
XS Rating Curve= 0 ,0
Exp/Cntr=0.3,0.1

Type RM Length L Ch R = 1 ,2407.1  ,278.7,289.7,300.7
XS GIS Cut Line= 4
     2323034.749      385229.238     2322916.767      385156.913
     2322635.506      385155.022      2322565.34      385125.254
#Sta/Elev= 30
       0  710.63    39.5  701.63    67.2  692.95      87  685.97   102.8   678.3
   118.6  671.38   146.3  661.45   158.2  660.03   193.8  659.41   201.8  658.45
   225.5  659.25   237.4  658.81   241.4  658.16   246.8  656.14   249.3  655.36
   257.2  654.79   265.2   656.1     277   657.7     285  658.18   304.8   657.5
   312.7  658.31   344.4  658.24   356.3  661.09   368.2  666.26   376.1  667.16
     388  667.17   406.8 668.315   427.3  669.89  490.42677.5911   495.9   678.7
#Mann= 5 ,-1 , 0
       0     .12       0   246.8    .045       0   265.2     .12       0
   406.8     .06       0  490.42    .016       0
Bank Sta=246.8,265.2
XS Rating Curve= 0 ,0
Exp/Cntr=0.3,0.1

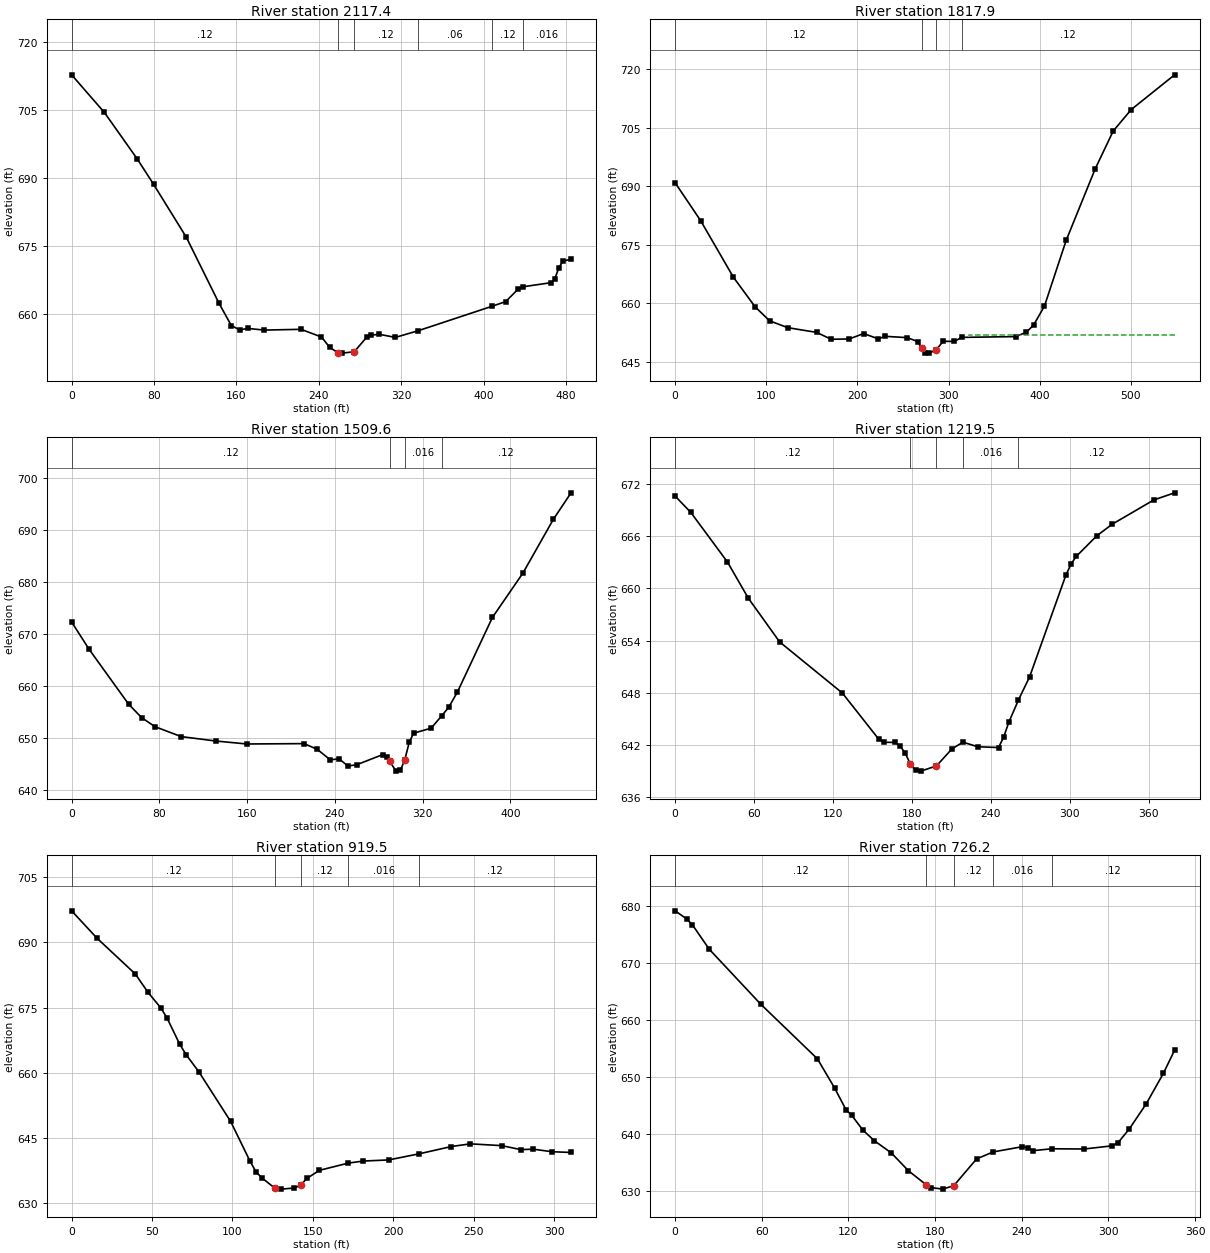
Type RM Length L Ch R = 1 ,2117.4  ,300.5,299.5,297.9
XS GIS Cut Line= 3
     2323079.249      384948.958     2322744.881      384845.994
     2322612.191      384869.998
#Sta/Elev= 30
       0  712.83    31.8  704.51    63.6  694.27    79.5  688.66   111.3  676.95
   143.1  662.33     155  657.44     163  656.49     171  656.81   186.9  656.44
   222.6  656.61   242.5  654.91   250.5  652.61   258.4  651.44   262.4  651.35
   274.3  651.65   286.2  654.83   290.2  655.28   298.2  655.53   314.1  654.82
  336.36656.2983   408.3661.7255   421.2  662.73   433.2  665.46  438.21666.0128
   464.9   666.9   468.8  667.68   472.8  670.16   476.8  671.69   484.7  672.09
#Mann= 6 ,-1 , 0
       0     .12       0   258.4    .045       0   274.3     .12       0
  336.36     .06       0   408.3     .12       0  438.21    .016       0
Bank Sta=258.4,274.3
XS Rating Curve= 0 ,0
Exp/Cntr=0.3,0.1

Type RM Length L Ch R = 1 ,1817.9  ,285,308.3,331.9
XS GIS Cut Line= 3
     2323144.365      384701.223     2323050.437      384627.244
     2322636.143       384517.86
#Sta/Elev= 30
       0  690.85    27.9  681.18    63.8  666.71    87.7   659.1   103.6  655.52
   123.5  653.76   155.3  652.55   171.1  650.79     191  650.87   206.8  652.25
   222.7  650.91   230.6  651.54   254.5  651.21   266.4  650.19   270.3  648.49
   274.3  647.32   278.3  647.24   286.2  648.03   294.1  650.28     306  650.23
  314.73651.2767   373.5  651.47   385.4  652.59   393.3  654.44   405.2  659.28
     429   676.1   460.8  694.38   480.6   704.1   500.4  709.61     548  718.51
#Mann= 4 ,-1 , 0
       0     .12       0   270.3    .045       0   286.2    .016       0
  314.73     .12       0
#XS Ineff= 2 , 0
       0                   321.9       0  651.76
Permanent Ineff=
       F       F
Bank Sta=270.3,286.2
XS Rating Curve= 0 ,0
Exp/Cntr=0.3,0.1

Type RM Length L Ch R = 1 ,1509.6  ,286.7,290.2,291.3
XS GIS Cut Line= 3
     2323230.949      384553.426     2323003.562      384274.813
     2322936.537      384206.716
#Sta/Elev= 30
       0  672.31      16  667.03      52  656.46    63.9  653.87    75.9  652.15
    99.9  650.23   131.9  649.37   159.8  648.81   211.8  648.88   223.8  647.79
   235.8  645.75   243.8  645.96   251.7  644.57   259.7   644.8   283.7  646.78
   287.7  646.23   289.8  645.48   295.7  643.58   299.7  643.75   303.7   645.8
   307.7  649.13   311.7  650.89   327.7  651.86  337.25654.2271   343.6  655.85
   351.6  658.81   383.5  673.18   411.4  681.76   439.2  692.14   455.2   697.2
#Mann= 4 ,-1 , 0
       0     .12       0   289.8    .045       0   303.7    .016       0
  337.25     .12       0
Bank Sta=289.8,303.7
XS Rating Curve= 0 ,0
Exp/Cntr=0.3,0.1

Type RM Length L Ch R = 1 ,1219.5  ,315.8,300,285.1
XS GIS Cut Line= 3
     2323405.364      384344.806     2323296.215       384183.68
     2323183.867      384036.769
#Sta/Elev= 30
       0  670.65    11.9  668.77    39.7  663.06    55.6  658.88    79.4  653.84
   127.1  647.94   154.9  642.59   158.9  642.27   166.8  642.25   170.8  641.87
   174.8  641.03   178.7  639.78   182.7  639.03   186.7  638.94   198.6  639.54
   210.4  641.51  218.75642.2776     230  641.75   245.8  641.66   249.7  642.87
   253.6  644.58  260.93647.1488   269.4  649.81   296.9  661.51   300.9  662.82
   304.8  663.69   320.5  666.08   332.3  667.42   363.8  670.21   379.6  671.03
#Mann= 5 ,-1 , 0
       0     .12       0   178.7    .045       0   198.6     .12       0
  218.75    .016       0  260.93     .12       0
Bank Sta=178.7,198.6
XS Rating Curve= 0 ,0
Exp/Cntr=0.3,0.1

Type RM Length L Ch R = 1 ,919.5   ,232.2,193.3,160.3
XS GIS Cut Line= 3
     2323600.449      384026.528     2323482.946       383953.33
     2323333.871      383867.317
#Sta/Elev= 30
       0  697.27    15.8  690.97    39.6  682.75    47.5  678.52    55.4  674.98
    59.3  672.65    67.2  666.61    71.2  664.19    79.1  660.27    98.9  648.84
   110.8  639.81   114.7  637.23   118.7  635.75   126.6  633.44   130.5  633.28
   138.4  633.54   142.4  634.17   146.3  635.75   154.1   637.6  172.04 639.264
   181.5  639.74   197.1  639.99  216.12641.3992   236.2  643.08     248  643.69
   267.5  643.28   279.2  642.37   287.1  642.46   298.8  641.88   310.6  641.71
#Mann= 5 ,-1 , 0
       0     .12       0   126.6    .045       0   142.4     .12       0
  172.04    .016       0  216.12     .12       0
Bank Sta=126.6,142.4
XS Rating Curve= 0 ,0
Exp/Cntr=0.3,0.1

Type RM Length L Ch R = 1 ,726.2   ,118,122.2,117
XS GIS Cut Line= 4
     2323714.029      383859.564     2323638.327      383768.737
     2323532.207      383798.034     2323435.459      383731.372
#Sta/Elev= 30
       0  679.15     7.9  677.74    11.8  676.75    23.6  672.42    59.1  662.83
    98.5  653.22   110.4  648.11   118.2  644.34   122.2  643.34     130  640.73
   137.9  638.88   149.7  636.73   161.5  633.62   173.9  631.14   177.2  630.68
   185.1   630.4   192.9     631   208.7  635.69  220.13636.9141   240.1  637.82
     244  637.69   247.9  637.14  260.62637.4666   283.2  637.43   302.7  637.99
   306.7  638.55   314.5  640.96   326.2  645.36     338  650.66   345.8  654.74
#Mann= 5 ,-1 , 0
       0     .12       0   173.9    .045       0   192.9     .12       0
  220.13    .016       0  260.62     .12       0
Bank Sta=173.9,192.9
XS Rating Curve= 0 ,0
Exp/Cntr=0.3,0.1

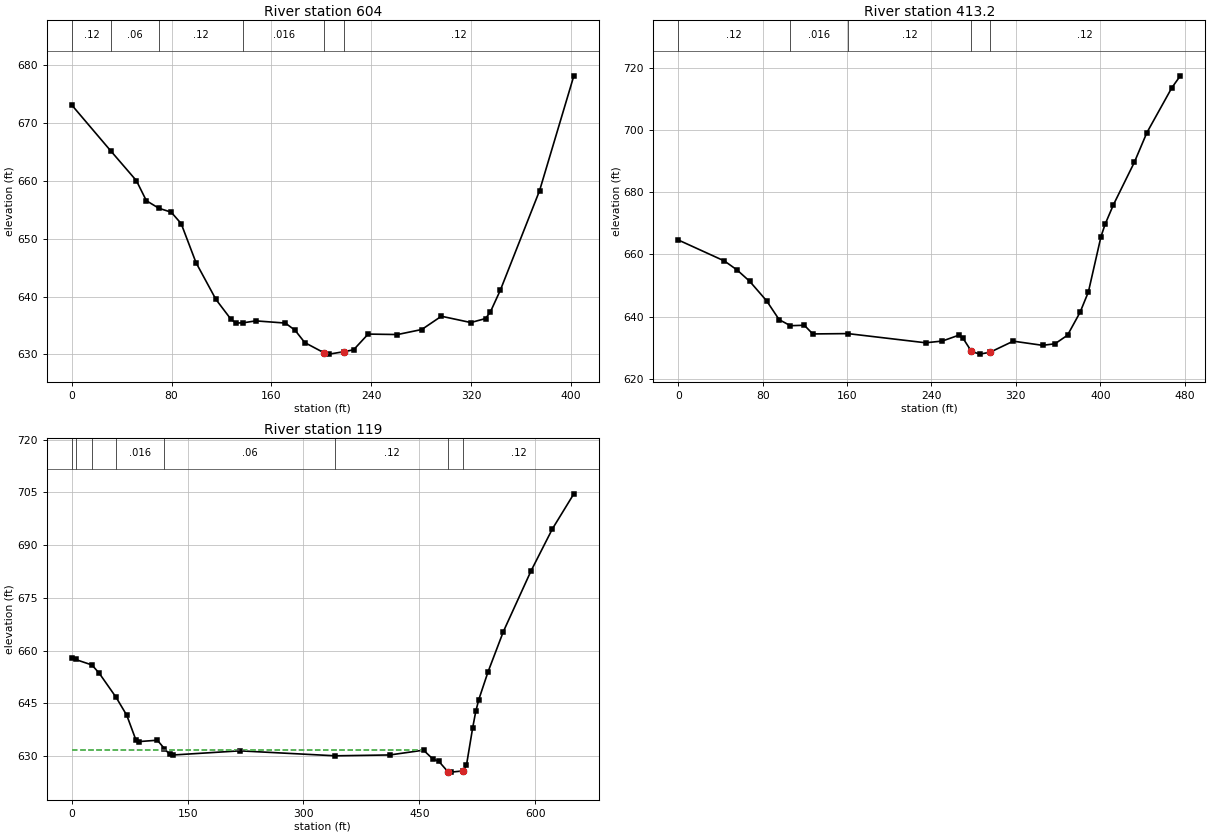
Type RM Length L Ch R = 1 ,604     ,153,190.8,233.4
XS GIS Cut Line= 4
     2323789.317      383796.939     2323688.891      383668.043
     2323564.108      383700.595       2323475.8      383634.817
#Sta/Elev= 30
       0  673.05    31.6665.0464    51.8     660    59.8  656.54    69.8655.2374
    79.7  654.56    87.7  652.59    99.6  645.85   115.6  639.49   127.5  636.11
   131.5  635.43   137.2635.4567   147.5   635.8   171.2  635.42     179  634.18
   186.8  632.05   202.5  630.26   206.4  630.06   218.1  630.48   225.9   630.8
   237.6  633.52   261.1  633.44   280.6  634.31   296.3   636.6   319.9  635.51
   331.7   636.2   335.6  637.35   343.5  641.06     375  658.26   402.5  678.09
#Mann= 6 ,-1 , 0
       0     .12       0    31.6     .06       0    69.8     .12       0
   137.2    .016       0   202.5    .045       0   218.1     .12       0
Bank Sta=202.5,218.1
XS Rating Curve= 0 ,0
Exp/Cntr=0.3,0.1

Type RM Length L Ch R = 1 ,413.2   ,289.5,294.2,298.8
XS GIS Cut Line= 3
     2323909.893      383744.712     2323875.957      383617.695
     2323598.732      383413.537
#Sta/Elev= 30
       0  664.63    43.8  657.86    55.8  654.97    67.7  651.34    83.7  645.08
    95.6  639.02  106.25637.0629   119.5   637.2   127.5  634.41  160.75634.5205
   234.4  631.57   250.2  632.12     266  634.02     270  632.96   277.9  628.78
   285.8  627.92   295.6  628.54   317.5  632.09   345.2  630.75     357  631.24
   368.9     634   380.8  641.36   388.7  647.93   400.6  665.68   404.5  669.65
   412.4  675.94   432.2  689.57   444.1  699.12   467.8  713.59   475.8   717.4
#Mann= 5 ,-1 , 0
       0     .12       0  106.25    .016       0  160.75     .12       0
   277.9    .045       0   295.6     .12       0
#XS Ineff= 2 , 0
       0     266  634.02               0
Permanent Ineff=
       F       F
Bank Sta=277.9,295.6
XS Rating Curve= 0 ,0
Exp/Cntr=0.3,0.1

Type RM Length L Ch R = 1 ,119     ,114.4,119,123.5
XS GIS Cut Line= 3
     2324106.222      383701.762     2323982.728      383367.695
     2323769.965      383164.984
#Sta/Elev= 30
       0  657.96    4.95657.5001   26.11655.9448    35.6  653.58   57.39646.7435
    71.2  641.65    83.1  634.58    87.1  634.17   110.8  634.56  119.95632.1694
   126.6  630.54   130.6  630.35   217.6  631.54  341.31630.1276   411.8  630.37
   455.4  631.73   467.4  629.23   475.3  628.53   487.2  625.54   491.2  625.49
   507.1  625.85     511  627.48     519  638.06     523  642.72   526.9  646.09
   538.8  653.92   558.7  665.41   594.4   682.6   622.2  694.61     650  704.58
#Mann= 8 ,-1 , 0
       0     .06       0    4.95    .016       0   26.11     .12       0
   57.39    .016       0  119.95     .06       0  341.31     .12       0
   487.2    .045       0   507.1     .12       0
#XS Ineff= 2 , 0
       0   451.5  631.76               0
Permanent Ineff=
       F       F
Bank Sta=487.2,507.1
XS Rating Curve= 0 ,0
Exp/Cntr=0.3,0.1

Chan Stop Cuts=-1
Use User Specified Reach Order=0
Composite Channel Slope=5